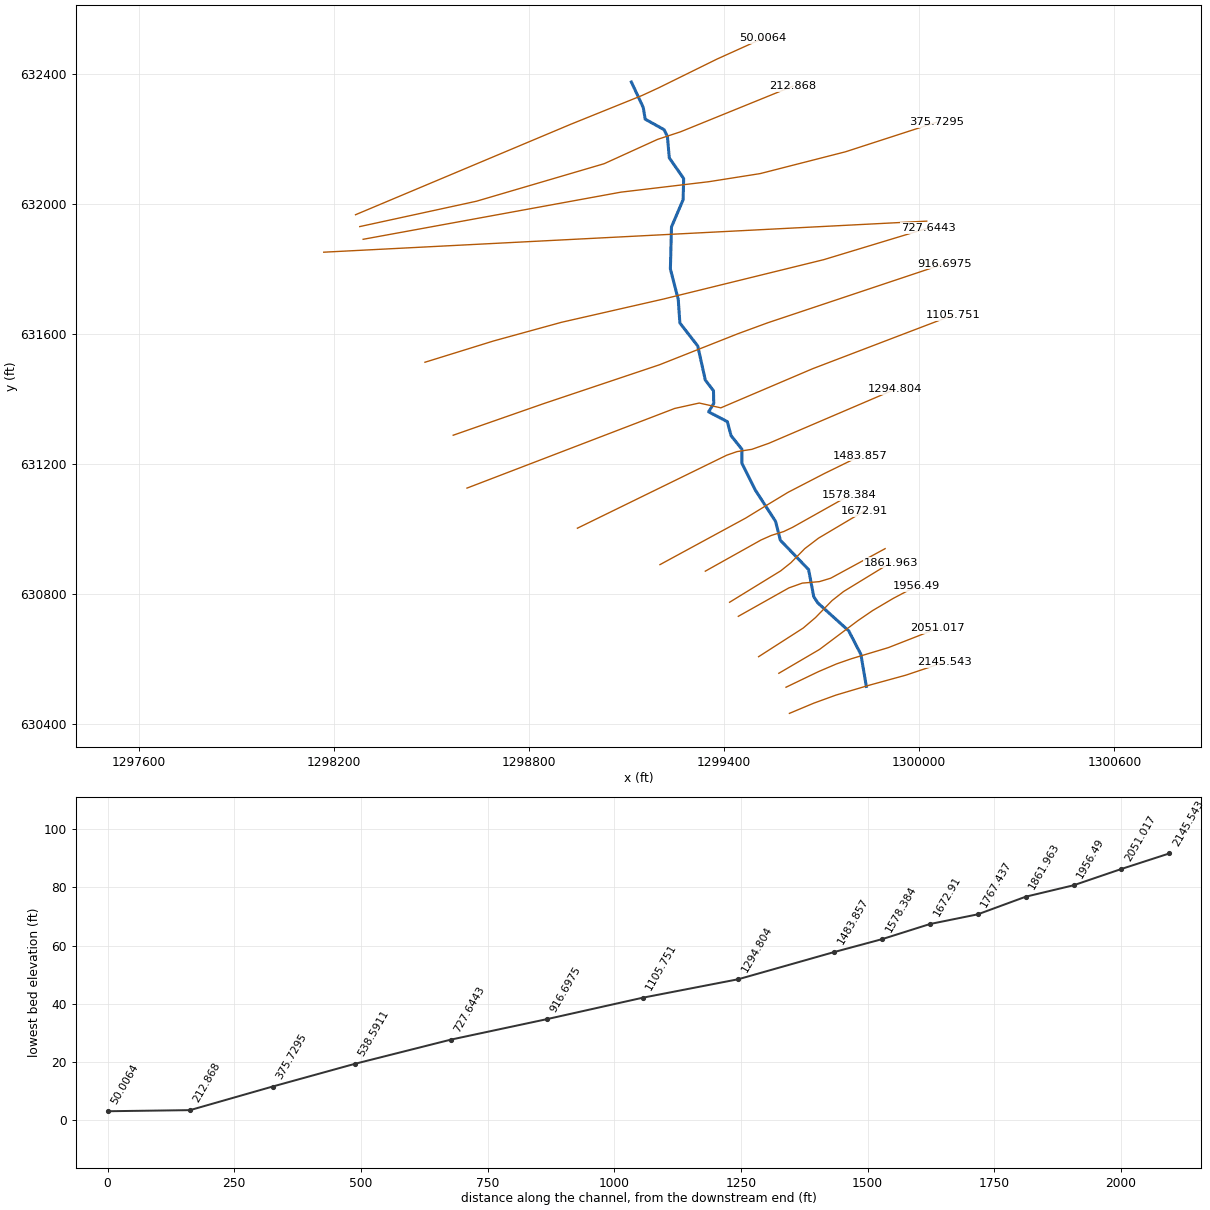
--- 795_ras.prj (project) ---

Proj Title=795
Current Plan=p01
Default Exp/Contr=0.3,0.1
English Units
Geom File=g01
Flow File=f01
Plan File=p01
Y Axis Title=Elevation
X Axis Title(PF)=Main Channel Distance
X Axis Title(XS)=Station
BEGIN DESCRIPTION:
RFD model 795 exported to HEC-RAS
END DESCRIPTION:

--- 795_ras.p01 (plan) ---

Plan Title=Plan 01
Program Version=4.10
Short Identifier=Plan 01
Geom File=g01
Flow File=f01
Subcritical Flow
Calc Critical at every XS
Secant Critical Depth

--- 795_ras.f01 (steady flow) ---

Flow Title=Flow 01
Program Version=5.01
Number of Profiles= 5
Profile Names=10yr,25yr,50yr,100yr,500yr
River Rch & RM=795,16,2145.543
  411.17  495.44     592   637.9  757.84
River Rch & RM=795,16,2051.017
  418.24  505.22  604.02  652.49  777.69
River Rch & RM=795,16,1861.963
  446.94  545.15  653.21  712.59  860.08
River Rch & RM=795,16,1767.437
  451.11  550.99   660.4  721.43  872.28
River Rch & RM=795,16,1578.384
  453.86  554.84  665.15  727.27  880.36
River Rch & RM=795,16,1483.857
  457.94  560.55   672.2  735.95  892.38
River Rch & RM=795,16,1294.804
  461.96   566.2  679.17  744.54  904.29
River Rch & RM=795,16,1105.751
  515.09  641.44  772.21  860.28 1066.67
River Rch & RM=795,16,916.6975
  571.16  722.09  872.28  986.73 1247.68
River Rch & RM=795,16,727.6443
  574.51  726.95  878.32  994.42  1258.8
River Rch & RM=795,16,538.5911
  584.85  741.96  896.99 1018.25 1293.33
River Rch & RM=795,16,375.7295
  586.24  743.98   899.5 1021.46 1297.99
River Rch & RM=795,16, 212.868
  648.92  835.84 1013.98 1168.88 1514.22
River Rch & RM=795,16, 50.0064
  714.17  932.86 1135.29  1327.4 1751.12
Boundary for River Rch & Prof#=795,16,1
Up Type= 0
Dn Type= 2
Boundary for River Rch & Prof#=795,16,2
Up Type= 0
Dn Type= 2
Boundary for River Rch & Prof#=795,16,2
Up Type= 0
Dn Type= 2
Boundary for River Rch & Prof#=795,16,2
Up Type= 0
Dn Type= 2
Boundary for River Rch & Prof#=795,16,2
Up Type= 0
Dn Type= 2

--- 795_ras.g01 (geometry) ---

Geom Title=795
Program Version=4.10

River Reach=795,16
Reach XY= 30
 1299837.2622507630515.5534152871299820.59559178630613.886719916
1299783.09560504630686.3866994691299688.09563557630772.220010153
1299675.59563984630791.3866714941299659.76231368630874.719980564
1299573.09567521630964.7199563981299558.09568134631023.053272858
1299495.59570267631119.7199126781299454.76238374631201.386556307
1299454.76238502 631244.71987678 1299421.4290628631286.386532026
1299409.76240082631329.7198528431299352.26241868631359.719845652
 1299368.0957481631385.553170867 1299367.2624162631424.719825883
1299342.26242451631457.2198169891299318.92910115631562.219786514
 1299263.9291195631633.0531004591299258.92912311631705.553079083
1299234.76246629631798.8863854091299238.09580249631928.053013639
1299273.92912772632012.2196542271299275.59579582632077.219634904
1299231.42914406632140.5529507541299225.59581436632206.386264723
1299215.59581793632227.219592128 1299157.2625028632259.719584218
1299151.42917222632295.5529070791299114.76251871632373.886218246

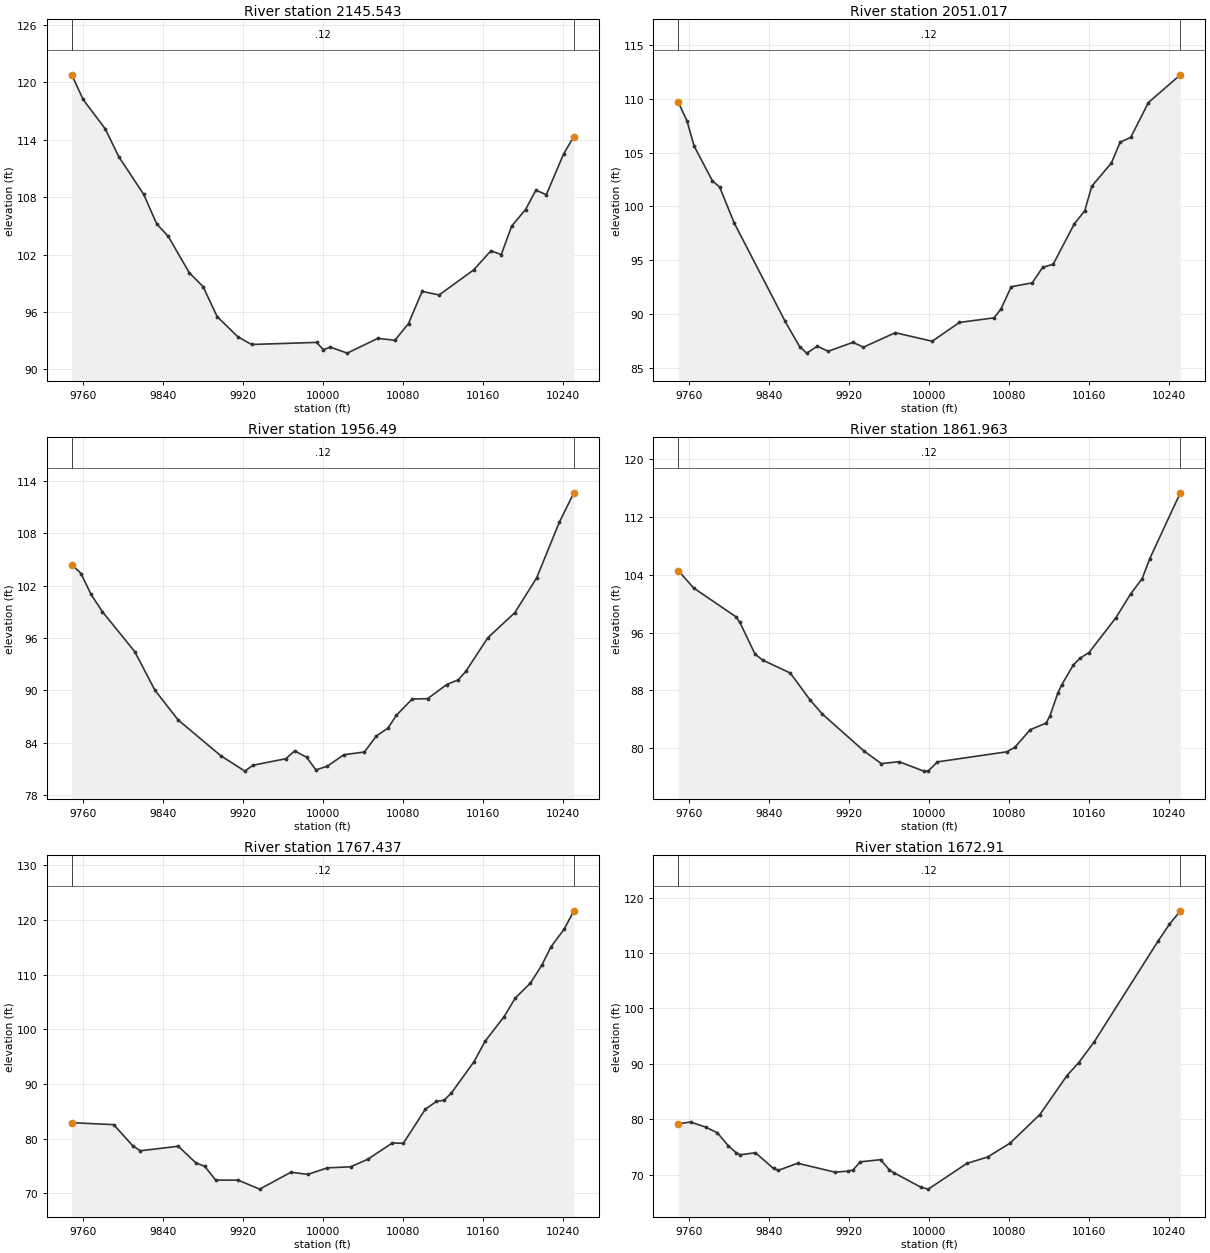
Type RM Length L Ch R = 1 ,2145.543,94.526600,94.526600,94.526600
XS GIS Cut Line= 6
1299600.71857102630432.6053539141299675.15369679630463.797521974
1299744.43073765630489.0012926471299846.41471574630519.240542576
1299959.19313314630550.2201578441300076.90368118630589.844655967
#Sta/Elev= 30
9749.021120.79629760.363118.21759782.556 115.1379795.936112.25689820.836108.3121
9833.979105.2075 9845.44103.91529866.387100.12099880.35298.646949894.31795.52691
9915.03393.411849928.72492.605239993.756 92.8214 10000.692.0539810007.4392.32962
10024.4591.7003610055.0793.2487410072.0893.0412610085.69 94.7967 10099.398.15636
10116.3197.7819210150.75100.396110168.06102.396210178.44102.004510188.83104.9907
10202.67106.707210213.06108.737410223.45 108.26610240.75 112.52710250.98 114.343
#Mann= 3 , 0 , 0
9749.021    0.12       09749.021    0.12       010250.98    0.12       0
#XS Ineff= 2 , 0
       09973.247        10047.76       0
Bank Sta=9749.021,10250.98
Exp/Cntr=0.3,0.1

Type RM Length L Ch R = 1 ,2051.017,94.526600,94.526600,94.526600
XS GIS Cut Line= 6
1299590.26255328630512.9764473481299689.84466174630560.850958904
1299745.49327333630584.6419764861299791.31418663 630600.59069931
1299905.18504235630634.8732303851300057.39011298630694.443333884
#Sta/Elev= 30
9749.032109.7041 9757.68107.9811 9764.96105.60449783.162102.38339790.442101.7985
9805.00398.458899855.96789.30487 9870.31  86.9779877.44686.361149888.15187.00533
9898.85586.530929923.73287.364639934.15386.913949966.05288.2606710002.9487.46528
10030.1689.2142110064.6989.64142 10071.6 90.453710081.9592.5322210102.8992.89577
 10113.494.3341310123.9194.6281310144.9298.3637210155.44 99.599910162.52101.8878
10182.08104.035810190.82105.973210201.43106.419910219.12  109.6610250.98112.2346
#Mann= 3 , 0 , 0
9749.032    0.12       09749.032    0.12       010250.98    0.12       0
#XS Ineff= 2 , 0
       09972.341        10032.51       0
Bank Sta=9749.032,10250.98
Exp/Cntr=0.3,0.1

Type RM Length L Ch R = 1 , 1956.49,94.526500,94.526500,94.526500
XS GIS Cut Line= 6
1299568.18966449630555.8716089991299693.21289756630629.137124979
1299811.24084918630717.6304487781299856.61667974630748.710949205
1299920.06401833630786.1891436631299991.53145013630823.824095238
#Sta/Elev= 30
 9749.02104.41529758.274103.39039768.211101.01919779.49399.037329811.97394.44591
9832.10990.03077 9855.3286.615779897.96982.513529922.08580.747619930.12481.42153
9963.05282.170139971.72883.063379983.83582.33831  9993.180.88947 10004.681.31513
10021.0482.62695 10041.682.9388310053.5384.7755510065.1785.6770310073.41 87.1283
10089.3289.0063410104.8689.0542810123.9190.6706810135.3491.2059510142.9692.17099
 10164.996.02348 10191.998.89714 10213.7102.870110236.39109.249210250.97112.6372
#Mann= 3 , 0 , 0
 9749.02    0.12       0 9749.02    0.12       010250.97    0.12       0
#XS Ineff= 2 , 0
       09974.786        10030.69       0
Bank Sta=9749.02,10250.97
Exp/Cntr=0.3,0.1

Type RM Length L Ch R = 1 ,1861.963,94.526600,94.526600,94.526600
XS GIS Cut Line= 6
1299506.03230362630606.8704312981299643.18518562630694.973308704
1299681.22771885630727.425743837 1299731.6392988 630779.26222082
1299767.29749024630807.3375151161299913.23288113630896.506996191
#Sta/Elev= 30
9749.061104.58879764.578102.16899806.73398.195049810.56597.446619825.89493.01169
9833.55992.193189861.07390.402199881.10186.627079893.11784.722479934.782 79.5965
9952.03177.864479969.96578.120879994.47476.81798 9999.0376.8558510008.1778.09917
10077.4279.4930210085.3980.1071710101.0282.5616310116.6583.4648610120.5384.42975
10128.3787.5709110132.2888.74757   1014491.5201310150.7392.4700810159.6393.23423
10186.26 98.006610201.42101.381410212.79103.471110220.37106.236410250.94115.3569
#Mann= 3 , 0 , 0
9749.061    0.12       09749.061    0.12       010250.94    0.12       0
#XS Ineff= 2 , 0
       09970.587        10061.24       0
Bank Sta=9749.061,10250.94
Exp/Cntr=0.3,0.1

Type RM Length L Ch R = 1 ,1767.437,94.526600,94.526600,94.526600
XS GIS Cut Line= 6
1299443.68256776630731.0613373111299599.34560712630818.523772774
1299640.45429986630833.1463160381299692.70834726630837.656239417
1299727.54550279630848.166728636 1299895.0310328630939.092626014
#Sta/Elev= 30
 9749.0582.915399790.97982.557249809.94678.702839817.532  77.7789855.46678.60908
9873.10675.556619881.859  74.9489892.94272.410059915.10972.419849936.90170.76443
9968.176  73.8639984.87773.45831 10004.674.6591610027.7974.8449310044.9276.22977
 10069.579.2125110080.4779.1455510102.43 85.3778 10113.486.7920110121.0987.01806
10128.3988.3184210150.9994.0431310162.2997.8458610181.12102.294210192.42105.7292
10207.49108.434810218.78 111.70110227.97115.046310241.33118.355610250.87121.6555
#Mann= 3 , 0 , 0
 9749.05    0.12       0 9749.05    0.12       010250.87    0.12       0
#XS Ineff= 2 , 0
       09961.199        10051.09       0
Bank Sta=9749.05,10250.87
Exp/Cntr=0.3,0.1

Type RM Length L Ch R = 1 , 1672.91,94.526600,94.526600,94.526600
XS GIS Cut Line= 6
1299416.80079737630774.2958480251299574.16945335630870.948689228
1299605.48880182 630895.95875511 1299647.9963148630939.150794191
1299690.42199557630971.4970105771299830.69549509631054.645262476
#Sta/Elev= 30
9749.05879.213969761.44179.523369776.698 78.58629788.14177.586759799.25375.21686
9807.21273.953319811.02673.620019826.28373.984629844.28271.148879849.16870.81472
9868.40472.091159905.68370.486089919.23170.678849923.77870.87938 9930.9672.34835
 9951.3572.735919960.14270.891779964.34170.410549991.489 67.7793    999967.42443
10037.4672.05499 10058.373.2186610080.7575.7167910110.5180.8712510137.6787.91199
10149.3190.2320910164.5593.8975110228.64112.144410239.95115.159710250.92117.6133
#Mann= 3 , 0 , 0
9749.058    0.12       09749.058    0.12       010250.92    0.12       0
#XS Ineff= 2 , 0
       09960.101        10048.28       0
Bank Sta=9749.058,10250.92
Exp/Cntr=0.3,0.1

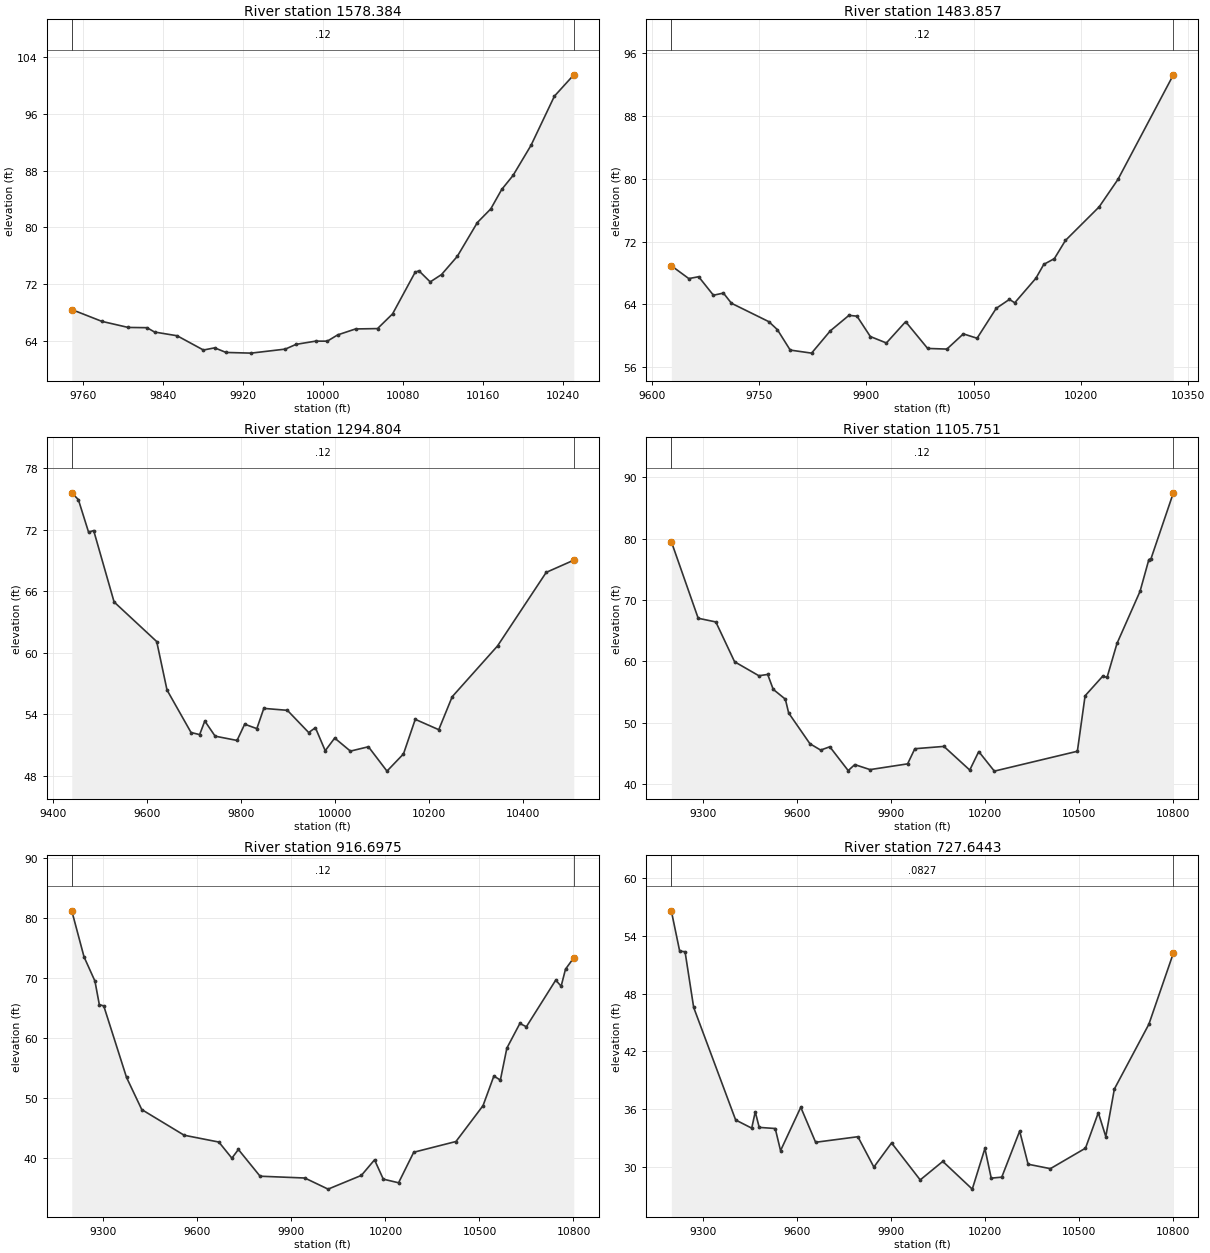
Type RM Length L Ch R = 1 ,1578.384,94.526600,94.526600,94.526600
XS GIS Cut Line= 6
 1299342.1095468630869.847345492 1299513.7361309630965.834622964
1299545.39294843630979.8697894531299583.14991609630991.682616183
1299610.26596812631004.5760809641299785.56613017631103.002243255
#Sta/Elev= 30
9749.04368.373959779.16366.705699805.47765.849229824.272 65.8138 9831.7965.20191
9854.34564.676779880.65962.662059891.936 62.96969903.21362.321279928.35962.22374
9962.55862.793199973.32563.463729992.93763.9181310004.51 63.911910014.8664.79523
10032.7665.6368610054.7265.6863510069.7767.7642310092.3573.6406510096.11 73.8459
 10107.472.2762410118.6973.3123810134.4475.8749810154.54 80.656710167.9582.58311
10178.8985.3276410190.1887.2954710208.1591.5436710231.5798.4931510250.96101.5041
#Mann= 3 , 0 , 0
9749.043    0.12       09749.043    0.12       010250.96    0.12       0
#XS Ineff= 2 , 0
       09973.075        10024.77       0
Bank Sta=9749.043,10250.96
Exp/Cntr=0.3,0.1

Type RM Length L Ch R = 1 ,1483.857,189.053200,189.053200,189.053200
XS GIS Cut Line= 6
1299202.66940385630889.9332457181299466.22967029631033.031171411
1299528.98698041631071.4289392081299596.53720295631112.303206876
1299708.33318782631170.1129038331299819.21188247631224.357513577
#Sta/Elev= 30
9627.52668.922319651.98167.287389665.73367.524829686.36165.167719700.37665.44055
9711.57664.144849763.84161.799179775.74760.784789793.70758.181659823.57357.79284
9849.70560.626829875.83862.606069887.03762.501389905.703 59.90639928.12359.08605
9955.04861.799329985.81958.39009 10012.758.3074910035.7160.2451210054.8959.68839
10081.6663.5003610100.1364.6384910107.5264.2040710137.0767.3252510148.1569.09709
10162.9269.8282310178.37 72.143110225.4976.4175810251.7879.9165410329.25 93.2398
#Mann= 3 , 0 , 0
9627.526    0.12       09627.526    0.12       010329.25    0.12       0
#XS Ineff= 2 , 0
       09956.048        10041.34       0
Bank Sta=9627.526,10329.25
Exp/Cntr=0.3,0.1

Type RM Length L Ch R = 1 ,1294.804,189.053200,189.053200,189.053200
XS GIS Cut Line= 6
1298948.86339229631001.9713256361299408.06774011631226.481713593
1299439.72385412631237.4895518871299485.27657214631244.477400854
1299537.69951472631263.1150025871299924.29153553631428.577649131
#Sta/Elev= 30
9440.08675.61119  9454.174.949799475.80371.772529486.65571.929089530.06164.96228
9620.63361.099069642.53656.371779693.64352.223819711.89652.022089722.84753.34852
9744.78851.86963  9791.451.451399807.60653.036749833.47352.604879848.25354.57981
 9898.3654.390559943.70752.221039957.94452.694819978.78550.448429998.936 51.6846
10032.3250.4104610070.6250.8363510110.0948.4577410145.1750.1404710170.1553.51199
10220.1152.5013810248.6655.7166910345.01 60.670510448.5167.8498710507.1669.04132
#Mann= 3 , 0 , 0
9440.086    0.12       09440.086    0.12       010507.16    0.12       0
#XS Ineff= 2 , 0
       09940.649        10019.69       0
Bank Sta=9440.086,10507.16
Exp/Cntr=0.3,0.1

Type RM Length L Ch R = 1 ,1105.751,189.053100,189.053100,189.053100
XS GIS Cut Line= 6
1298609.37857047631125.293131795 1299248.0966924631370.227425623
1299323.56222085631386.8368612941299389.79389868631372.041704078
1299672.58618459631492.5300930961300104.31348608631657.342788805
#Sta/Elev= 30
9199.18379.516889284.88967.014089341.20666.411329401.04359.921019478.47857.64127
9506.63757.852889524.23655.424749562.95453.820289573.51351.571079641.40646.55556
9675.58745.520629704.81546.061519763.43842.177679784.38243.153269833.25242.33855
9952.98643.276269976.08645.74505 10068.846.1198110151.2642.2636410179.9445.28286
 10229.742.0903910494.5745.3302710519.2154.3728310575.32  57.56410589.3457.37506
 10620.962.8990410694.5371.4040710722.5876.5740910729.5976.7453210800.7987.46187
#Mann= 3 , 0 , 0
9199.183    0.12       09199.183    0.12       010800.79    0.12       0
#XS Ineff= 2 , 0
       09976.297        10076.88       0
Bank Sta=9199.183,10800.79
Exp/Cntr=0.3,0.1

Type RM Length L Ch R = 1 ,916.6975,189.053200,189.053200,189.053200
XS GIS Cut Line= 6
1298566.96607365631287.865384713 1298844.5422525631384.832899855
 1299201.3816727631504.5155146751299441.97095622 631599.76360443
1299534.09259827631633.5731381621300079.14526508631815.654034725
#Sta/Elev= 30
9199.01181.148949238.20173.462199272.95469.429569286.85565.520179301.14665.27481
9373.73753.36322 9422.3947.992859557.64943.717059668.38342.577329709.90939.89095
9730.67141.33839 9799.8836.87995 9942.6936.5784810016.9134.7250210123.1437.01689
10165.1439.61195 10193.136.3871910241.8535.7848110290.2240.8786610424.9842.66951
10511.3648.6541110545.9153.5892610566.6452.9177910587.3758.2470410628.8462.35879
10649.6361.8137310743.2869.5868210760.6268.58089 10774.5 71.418110800.9973.32267
#Mann= 3 , 0 , 0
9199.011    0.12       09199.011    0.12       010800.99    0.12       0
#XS Ineff= 2 , 0
       09936.991        10134.28       0
Bank Sta=9199.011,10800.99
Exp/Cntr=0.3,0.1

Type RM Length L Ch R = 1 ,727.6443,189.053200,189.053200,189.053200
XS GIS Cut Line= 6
1298480.07600374631512.2479091311298690.72403522631577.575977091
1298899.60397359631635.0169947051299213.87064381631706.699621362
1299706.61857928631827.7566564571300026.85865843631924.823526357
#Sta/Elev= 30
9199.02656.580239225.68552.40069 9242.8652.334049270.33946.558249404.30434.87839
9455.59134.029549466.84435.724999479.47734.109079530.60133.991989547.57531.69487
9612.07436.197549659.45932.564079794.32333.141129845.328 29.98919901.80532.49515
9993.17228.6574710065.2330.5800410159.3227.7027510199.64 31.9218 10219.828.84307
 10253.428.9447210310.5333.7248310337.4830.28613 10408.529.8260610520.5731.95178
 10561.535.6321310585.3733.1550610612.7138.0906310722.8444.8149410800.9652.19078
#Mann= 3 , 0 , 0
9199.026  0.0827       09199.026  0.0827       010800.96  0.0827       0
#XS Ineff= 2 , 0
       09965.953        10072.96       0
Bank Sta=9199.026,10800.96
Exp/Cntr=0.3,0.1

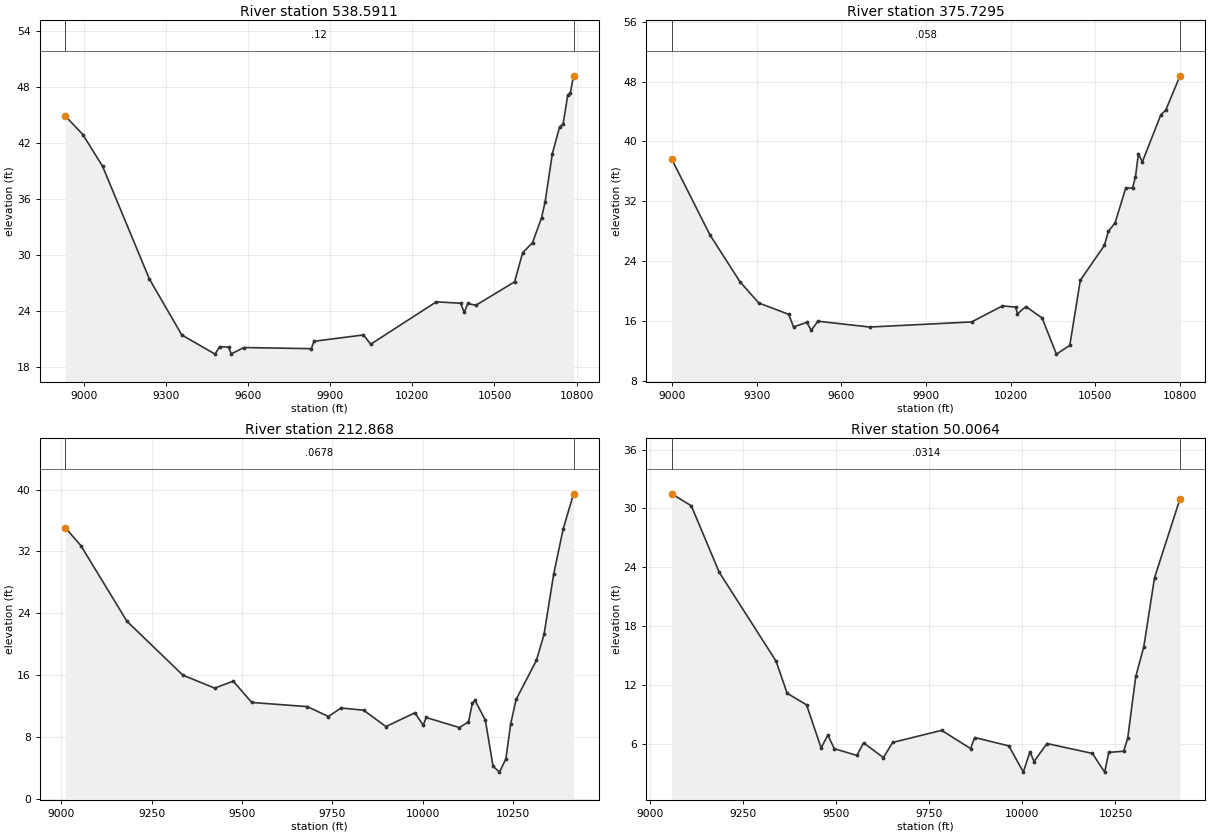
Type RM Length L Ch R = 1 ,538.5911,162.861600,162.861600,162.861600
XS GIS Cut Line= 2
1298168.88362914631850.638454452 1300023.0502958631946.124565542
#Sta/Elev= 30
8932.16944.93374  8996.642.938549068.87439.524079239.70327.45297 9357.9721.45975
9479.52119.404719495.94720.201639528.79920.160079538.65419.430499584.64720.11101
9831.036 19.98949840.89120.7842610021.5821.4608310047.8620.4669410287.6825.00845
10376.3824.8592910389.5223.8734710402.6624.8319910432.2224.6419410573.4927.15206
10603.0530.2765810639.1931.3540610672.0434.0314210685.1835.7580610711.4640.89656
10737.7543.7260210750.8944.0959610767.3147.1276310777.1747.4226710788.7949.23082
#Mann= 3 , 0 , 0
8932.169    0.12       08932.169    0.12       010788.79    0.12       0
#XS Ineff= 2 , 0
       09933.623        10043.22       0
Bank Sta=8932.169,10788.79
Exp/Cntr=0.3,0.1

Type RM Length L Ch R = 1 ,375.7295,162.861500,162.861500,162.861500
XS GIS Cut Line= 6
 1298290.0641847631890.3085933181299082.63347659 632035.25471203
1299352.91041443632067.3776026371299510.84874117632092.313397825
1299773.31838849632159.4297185691300053.00719893632250.104184851
#Sta/Elev= 30
8998.01437.657149133.55627.525319240.18621.256649306.82918.412649413.459 16.8902
 9430.1215.20935 9476.77 15.81249493.43114.776379516.75615.975889700.594  15.195
 10061.915.8779510171.2418.0195210217.88 17.862410224.5516.9795510254.6817.92867
10311.7916.4055610362.5811.57488   1041012.7381510447.4821.4512410532.9726.11791
 10546.727.9729710570.7429.1192510608.52 33.778310632.6633.7683910643.0335.27094
10653.4138.3735710667.2437.2543710732.95 43.555510750.2444.1728110800.9748.77155
#Mann= 3 , 0 , 0
8998.014   0.058       08998.014   0.058       010800.97   0.058       0
#XS Ineff= 2 , 0
       09951.465        10061.86       0
Bank Sta=8998.014,10800.97
Exp/Cntr=0.3,0.1

Type RM Length L Ch R = 1 , 212.868,162.861600,162.861600,162.861600
XS GIS Cut Line= 6
1298279.64751804631929.3710933181298638.07512757632007.272686526
1299030.98372942632122.6887888311299195.35805961632197.517132059
1299266.14779523632220.8753984121299611.86042061632361.321592852
#Sta/Elev= 30
9011.45535.079229054.60432.758859182.18622.967229336.62816.004469424.66714.32795
9475.85115.229189527.03512.473819680.63111.940369739.10110.655229773.49411.75913
9836.31911.474389897.7999.358976 9978.0211.13373   100019.53277310009.1310.53105
10101.039.22944610126.099.96399910136.83 12.382710143.9912.7605410172.6410.19283
10193.94 4.2375610211.663.46922310229.375.17437910242.639.69634510257.72 12.8617
10313.8817.9253110334.9421.2844510361.6829.0999310387.5934.8719710416.3939.44364
#Mann= 3 , 0 , 0
9011.455  0.0678       09011.455  0.0678       010416.39  0.0678       0
#XS Ineff= 2 , 0
       09949.427        10041.89       0
Bank Sta=9011.455,10416.39
Exp/Cntr=0.3,0.1

Type RM Length L Ch R = 1 , 50.0064,0.000000,0.000000,0.000000
XS GIS Cut Line= 6
1298266.62668473631965.8294266761298928.74516681632244.122491613
1299147.64065844632332.4781489971299198.89080313632356.124670163
1299378.02536502632444.4075026361299519.37354377632508.215068191
#Sta/Elev= 30
9057.856 31.4851  9110.6 30.26349185.33523.501759338.36614.40792 9367.9511.14027
9420.2199.9556969459.3675.5553029477.1616.8694489494.9595.4778749555.4564.791807
 9573.256.0822559626.6324.5705879651.5446.1210289783.0947.3523159860.9975.489927
9871.6096.6225429963.5765.76661110002.493.104184 10020.45.17725710031.244.171942
10065.926.00945110188.064.99839610220.983.09020310231.955.10355110272.125.225019
10282.92 6.5388710304.5212.8513110326.1215.8825710354.9122.9141210423.3730.98195
#Mann= 3 , 0 , 0
9057.856  0.0314       09057.856  0.0314       010423.37  0.0314       0
#XS Ineff= 2 , 0
       09929.845        10056.19       0
Bank Sta=9057.856,10423.37
Exp/Cntr=0.3,0.1